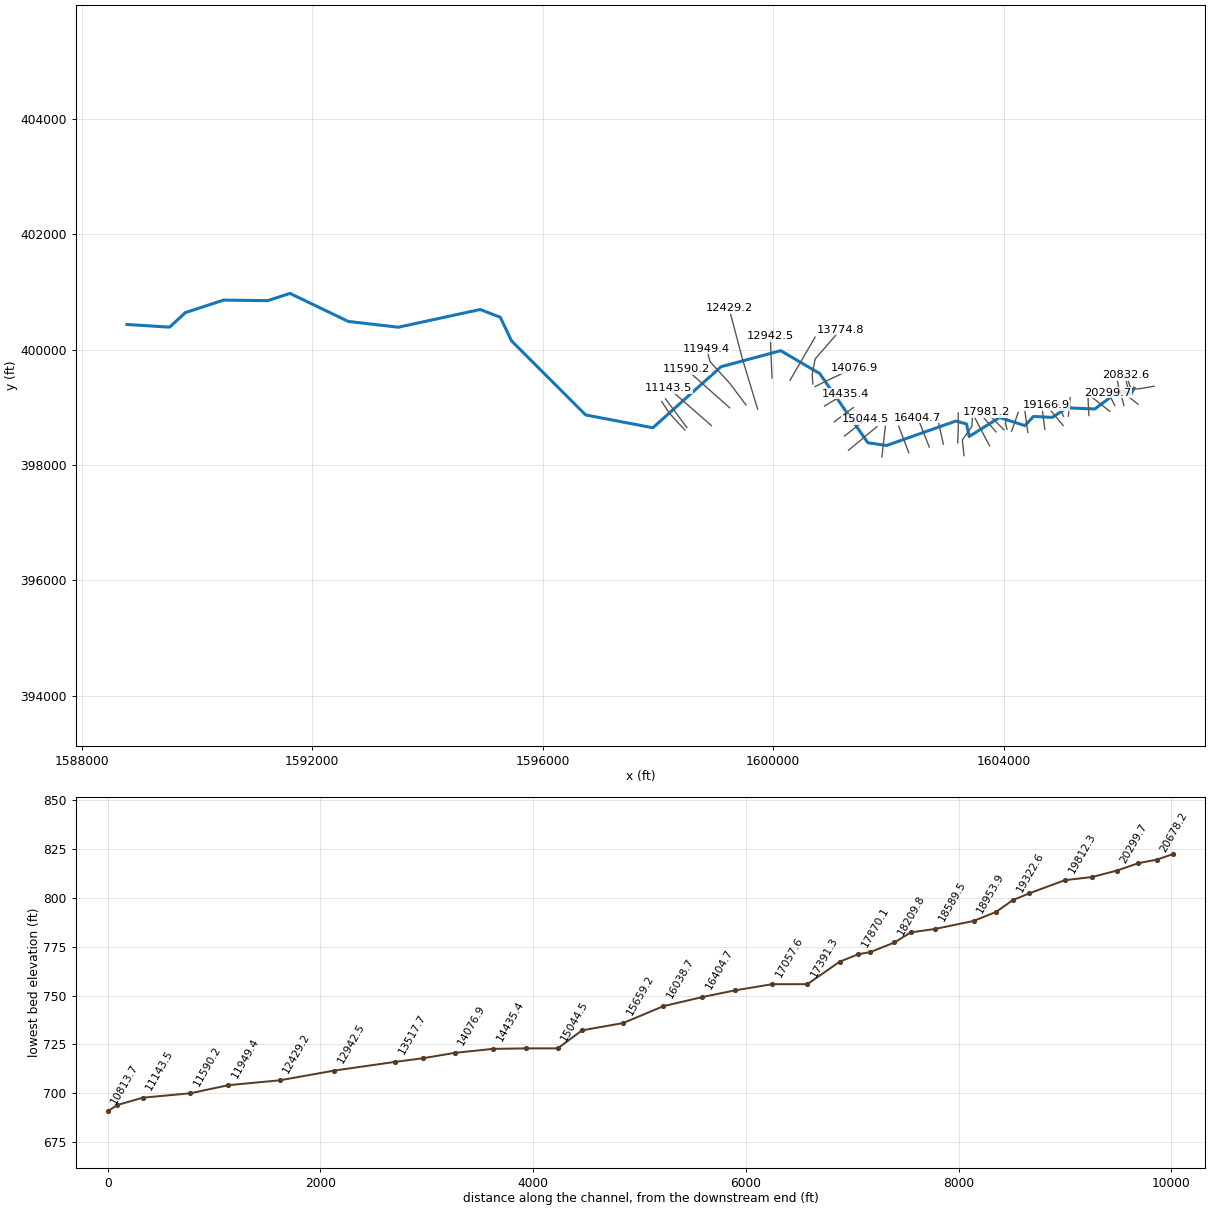
--- COVECR.prj (project) ---

Proj Title=COVECR
Current Plan=p01
Default Exp/Contr=0,0
English Units
Geom File=g01
Flow File=f01
Plan File=p01
BEGIN DESCRIPTION:
END DESCRIPTION:
DSS Export Rating Curves= 0
DSS Export Rating Curve Sorted= 0
DSS Export Volume Flow Curves= 0
DXF OffsetX= 0
DXF OffsetY= 0
DXF ScaleX= 0
DXF ScaleY= 0

--- COVECR.p01 (plan) ---

Plan Title=Floodplain
Program Version=4.00
Geom File=g01
Flow File=f01
K Sum by GR=0
Std Step Tol=0.01
Critical Tol=0.01
Num of Std Step Trials=20
Max Error Tol=0.3
Flow Tol Ratio=0.001
Split Flow NTrial=30
Split Flow Tol=0.02
Split Flow Ratio=0.02
Log Output Level=0
Friction Slope Method=1
Unsteady Friction Slope Method=2
Unsteady Bridges Friction Slope Method=1
Global Log Level=0
CheckData=False
Run HTab=0
Run UNet=0
Run PostProcess=0
UNET Theta=0
UNET Theta Warmup=0
UNET ZTol=0
UNET ZSATol=0
UNET MxIter=0
UNET MaxInSteps=0
UNET DtIC=0
UNET DtMin=0
UNET MaxCRTS=0
UNET WFStab=0
UNET SFStab=0
UNET WFX=0
UNET SFX=0
UNET DSS MLevel=0
UNET DZMax Abort=0
UNET Convert EG Bridges=0
UNET Use Existing IB Tables=0
UNET Froude Limit=0
UNET Froude Power=0
Write IC File=0
Echo Input=False
Echo Output=False
Write Detailed=0

--- COVECR.f01 (steady flow) ---

Flow Title=NFF Regression Equation
Program Version=4.00
Number of Profiles=1
Profile Names=P100yr
River Rch & RM=COVECR,Main      ,20832.6
346.9716
River Rch & RM=COVECR,Main      ,20678.2
526.4671
River Rch & RM=COVECR,Main      ,19474.3
547.3861
River Rch & RM=COVECR,Main      ,17694.4
606.4020
River Rch & RM=COVECR,Main      ,17391.3
665.7343
River Rch & RM=COVECR,Main      ,16709.3
674.3732
River Rch & RM=COVECR,Main      ,14076.9
748.4840
River Rch & RM=COVECR,Main      ,13774.8
915.3921
River Rch & RM=COVECR,Main      ,10488.4
997.9239
River Rch & RM=COVECR,Main      ,9879.8
1091.136
River Rch & RM=COVECR,Main      ,8670.2
1162.038
Boundary for River Rch & Prof#=COVECR,Main      ,1
Up Type=0
Dn Type=3
Dn Slope=0.010538

--- COVECR.g01 (geometry) ---

Geom Title=Geometry
Program Version=4.00

River Reach=COVECR          ,Main
Reach XY= 30
     1606266.697      399329.316     1606213.672      399231.909
     1606011.408      399292.043     1605583.259      398970.458
     1605100.887      398990.335     1604847.783      398825.044
     1604519.807      398841.239     1604371.342      398682.218
     1603929.703      398823.231     1603404.083      398493.123
      1603357.85      398711.031     1603173.268      398762.093
      1601971.55      398337.559     1601644.872      398385.395
       1600809.4      399585.473     1600133.116      399981.737
     1599096.645      399702.913     1597914.851      398644.774
     1596749.648      398866.665     1595461.098      400151.865
     1595267.748      400560.673     1594919.414      400695.892
     1593497.688      400388.801     1592630.322      400488.649
     1591616.415      400975.142     1591229.949      400848.972
     1590466.109      400859.202     1589802.295      400642.099
     1589528.359      400389.759     1588789.309       400436.23

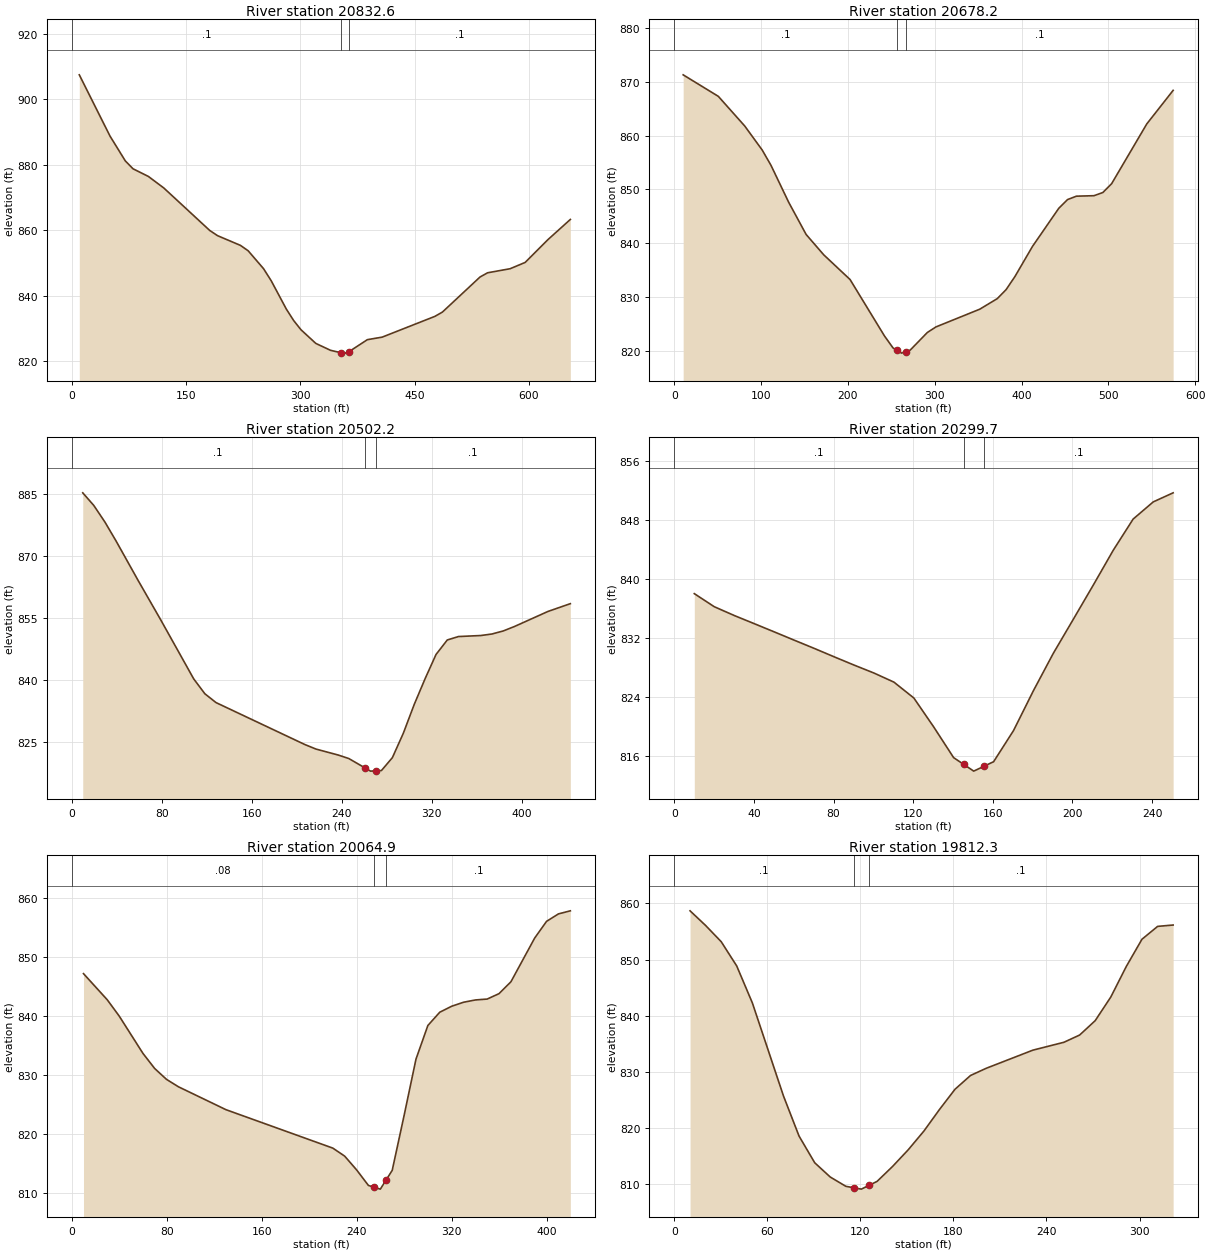
Type RM Length L Ch R = 1 ,20832.6 ,184.7,154.4,124.5
XS GIS Cut Line= 4
     1606612.478       399364.78     1606344.275      399319.637
     1606208.846      399324.948     1606129.182       399558.63
#Sta/Elev= 30
    10.1  907.47    50.4  888.77    70.5  881.19    80.6  878.79   100.7  876.46
   120.9  872.95   181.3  859.96   191.4  858.39   221.6  855.41   231.7  853.76
   251.8  848.32   261.9  844.62   281.7  835.99   291.3   832.5     301  829.66
   320.4   825.5   339.7  823.39   354.1  822.62   359.1  822.53   364.1     823
   388.1  826.64   407.5  827.41   476.6  833.74   486.5  835.05   535.9  845.76
   545.8  847.05   575.4  848.29   595.1  850.21   624.8  857.13   654.4  863.33
#Mann= 3 , 0 , 0
       0      .1       0   354.1    .045       0   364.1      .1       0
Bank Sta=354.1,364.1
XS Rating Curve= 0 ,0
Exp/Cntr=0.3,0.1

Type RM Length L Ch R = 1 ,20678.2 ,170.4,176,181.3
XS GIS Cut Line= 4
     1606333.654       399054.09     1606174.325      399178.897
      1606171.67      399287.772     1606105.283      399542.697
#Sta/Elev= 30
    10.1  871.25    50.6  867.26      81  861.77   101.2   857.3   111.3  854.47
   131.6  847.65   151.8  841.65     172  837.89   202.4   833.3     242  822.85
   251.9  820.62   256.8  820.14   261.8  819.65   266.8  819.93   271.7  820.21
   291.5  823.48   301.4  824.51   351.8  827.79   372.1  829.76   382.2  831.42
   392.4  833.85   412.6  839.43     443  846.52   453.1  848.13   463.3  848.75
   483.5  848.84   493.7  849.43   503.8  851.06   544.3  862.14   574.7  868.37
#Mann= 3 , 0 , 0
       0      .1       0   256.8    .045       0   266.8      .1       0
Bank Sta=256.8,266.8
XS Rating Curve= 0 ,0
Exp/Cntr=0.3,0.1

Type RM Length L Ch R = 1 ,20502.2 ,199.6,202.5,205.5
XS GIS Cut Line= 4
      1606089.35      399030.191     1606033.585      399239.973
     1605999.064      399340.881     1605975.165      399457.722
#Sta/Elev= 30
     9.9  885.35    19.7  882.29    29.6  878.26    39.5  873.66    59.2  864.03
    78.9  854.65   108.5  840.18   118.4  836.58   128.3  834.44   207.2  824.26
   217.1  823.16   236.5  821.74   246.2  820.87   260.5  818.61   265.5  817.81
   270.5  817.89   275.2  817.95   284.9  821.07   294.6  826.97   304.3  833.97
     314  840.25   323.7  846.12   333.7  849.64   343.6  850.47   363.5  850.72
   373.4  851.09   383.3  851.82   393.3   852.9   423.1  856.56     443  858.45
#Mann= 3 , 0 , 0
       0      .1       0   260.5    .045       0   270.5      .1       0
Bank Sta=260.5,270.5
XS Rating Curve= 0 ,0
Exp/Cntr=0.3,0.1

Type RM Length L Ch R = 1 ,20299.7 ,226,234.7,243.5
XS GIS Cut Line= 2
     1605930.022      399032.846     1605815.837      399255.906
#Sta/Elev= 27
      10  838.05      20  836.28    30.1  835.08    40.1  833.98    50.1  832.87
    60.1  831.75    70.2  830.63    80.2  829.49    90.2  828.37   100.2  827.29
   110.3  826.05   120.3   823.9   130.3  819.97   140.3  815.81   145.4  814.89
   150.4  813.98   155.4  814.62   160.4  815.26   170.4  819.48   180.4  824.89
   190.4  829.96   200.5   834.6   210.5  839.22   220.5  843.93   230.5  848.16
   240.6  850.49   250.6  851.72
#Mann= 3 , 0 , 0
       0      .1       0   145.4    .045       0   155.4      .1       0
Bank Sta=145.4,155.4
XS Rating Curve= 0 ,0
Exp/Cntr=0.3,0.1

Type RM Length L Ch R = 1 ,20064.9 ,270.4,252.6,234.9
XS GIS Cut Line= 2
     1605845.047      398929.283     1605515.768      399189.519
#Sta/Elev= 30
      10  847.21      30  842.78      40  840.04      60  833.71    69.9  831.14
    79.9  829.29    89.9  828.04   129.9  824.16   219.8  817.65   229.8  816.29
   239.8  813.97   249.8  811.32   254.8  811.01   259.8   810.7   264.8  812.29
   269.8  813.88   279.8  823.17   289.8  832.72   299.8  838.42   309.8  840.67
   319.8  841.68   329.8  842.36   339.8  842.75   349.7   842.9   359.7  843.82
   369.7  845.83   389.7  853.24   399.7  856.07   409.7  857.33   419.7  857.85
#Mann= 3 , 0 , 0
       0     .08       0   254.8    .045       0   264.8      .1       0
Bank Sta=254.8,264.8
XS Rating Curve= 0 ,0
Exp/Cntr=0.3,0.1

Type RM Length L Ch R = 1 ,19812.3 ,341.2,338,334.8
XS GIS Cut Line= 2
     1605481.247      398857.585     1605465.314      399178.897
#Sta/Elev= 30
    10.1  858.69    20.1  856.09    30.2  853.19    40.2  848.87    50.3  842.28
    70.4  825.68    80.4  818.57    90.5  813.82   100.5  811.28   110.6  809.62
   115.6  809.37   120.6  809.12   125.6   809.8   130.7  810.49   140.7  813.15
   150.8  816.12   160.9  819.45   170.9  823.27     181  826.91     191  829.36
   201.1  830.64   231.2  833.87   251.3  835.28   261.4  836.57   271.4  839.12
   281.5  843.34   291.5  848.79   301.6  853.63   311.7  855.92   321.7  856.16
#Mann= 3 , 0 , 0
       0      .1       0   115.6    .045       0   125.6      .1       0
Bank Sta=115.6,125.6
XS Rating Curve= 0 ,0
Exp/Cntr=0.3,0.1

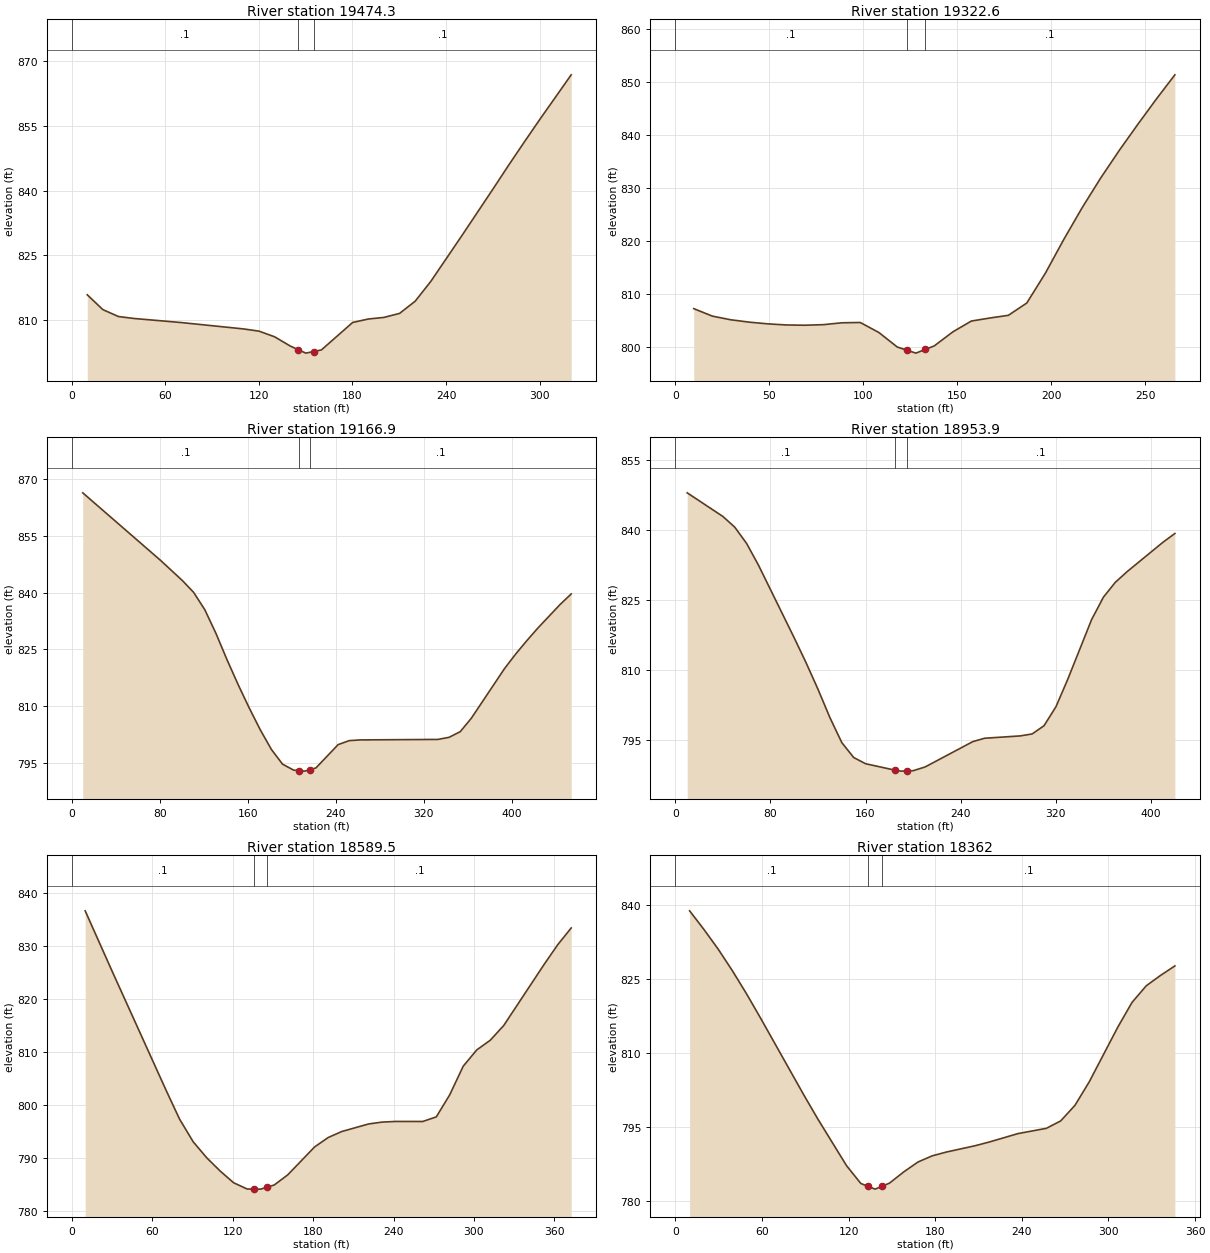
Type RM Length L Ch R = 1 ,19474.3 ,142,151.7,161.4
XS GIS Cut Line= 2
     1605125.414      398846.963      1605157.28       399165.62
#Sta/Elev= 25
      10  815.84      20   812.4      30  810.79      40  810.34    70.1   809.4
   110.1  807.92   120.1   807.4   130.1  806.09   140.1  803.95   145.1  803.13
   150.1   802.3   155.1  802.67   160.1  803.04   180.1  809.41   190.1  810.21
   200.2  810.59   210.2  811.52   220.2  814.35   230.2  818.94   250.2   829.6
   270.2  840.45   280.2  845.96   290.2  851.32   300.2  856.59   320.2  866.88
#Mann= 3 , 0 , 0
       0      .1       0   145.1    .045       0   155.1      .1       0
Bank Sta=145.1,155.1
XS Rating Curve= 0 ,0
Exp/Cntr=0.3,0.1

Type RM Length L Ch R = 1 ,19322.6 ,149.4,155.7,162
XS GIS Cut Line= 2
     1605040.439      398841.653     1604942.186      399088.611
#Sta/Elev= 29
     9.8  807.29    19.7  805.88    29.5  805.19    39.4  804.74    49.2  804.42
    59.1  804.21    68.9  804.16    78.8  804.27    88.6  804.62    98.4  804.68
   108.3  802.79   118.1  800.05     123  799.48     128   798.9     133   799.6
   137.8  800.27   147.7  802.92   157.5  804.95   167.3  805.52   177.2  806.03
     187  808.35   196.9  813.98   206.7  820.35   216.6  826.41   226.4  831.97
   236.3  837.18   246.1  842.06   255.9   846.8   265.8  851.39
#Mann= 3 , 0 , 0
       0      .1       0     123    .045       0     133      .1       0
Bank Sta=123,133
XS Rating Curve= 0 ,0
Exp/Cntr=0.3,0.1

Type RM Length L Ch R = 1 ,19166.9 ,224.3,213,201.7
XS GIS Cut Line= 2
     1605035.128       398684.98     1604743.026      399032.846
#Sta/Elev= 30
    10.1  866.35    80.8  848.53   100.9  843.13     111  840.04   121.1  835.48
   131.2  829.25   141.3  822.27   151.4  815.71   161.5  809.54   171.6  803.74
   181.7  798.57   191.8  794.71   201.9  793.14     207  793.01     212  792.88
     217   793.3   222.1  793.72   242.3  799.88   252.4  800.93   262.5  801.12
   333.1  801.25   343.2  801.81   353.3  803.29   363.4  806.84   393.7     820
   403.8  823.82   413.9  827.34     424  830.68   444.1  836.87   454.2  839.65
#Mann= 3 , 0 , 0
       0      .1       0     207    .045       0     217      .1       0
Bank Sta=207,217
XS Rating Curve= 0 ,0
Exp/Cntr=0.3,0.1

Type RM Length L Ch R = 1 ,18953.9 ,368.1,364.3,355.5
XS GIS Cut Line= 2
     1604716.471      398618.593     1604663.362      399035.502
#Sta/Elev= 30
      10  848.03      40  842.95      50  840.65      60  837.14      70  832.46
   100.1  816.82   110.1  811.46   120.1  805.77   130.1  799.69   140.1  794.32
   150.1  791.13   160.1   789.8   185.1   788.4   190.1  788.21   195.1  788.26
   200.1   788.3   210.1   789.1   250.2  794.54   260.2  795.28   290.2  795.78
   300.2   796.2   310.2  797.97   320.2  802.03   330.2  807.97   350.2  820.76
   360.2  825.61   370.2   828.8   380.3  831.13   410.3  837.41   420.3  839.29
#Mann= 3 , 0 , 0
       0      .1       0   185.1    .045       0   195.1      .1       0
Bank Sta=185.1,195.1
XS Rating Curve= 0 ,0
Exp/Cntr=0.3,0.1

Type RM Length L Ch R = 1 ,18589.5 ,233.7,227.5,226.6
XS GIS Cut Line= 2
     1604421.714      398562.828      1604371.26      398931.938
#Sta/Elev= 30
    10.1  836.57    30.2  825.18    70.5   802.7    80.5  797.29    90.6  793.04
   100.7  790.02   110.8   787.5   120.8   785.3   130.9  784.12     136  784.11
     141   784.1     146  784.49     151  784.87   161.1  786.78   181.2  792.06
   191.3  793.83   201.4  794.96   221.5  796.39   231.6  796.74   241.6  796.86
   261.8  796.85   271.9  797.72   281.9  801.87     292  807.28   302.1  810.35
   312.1  812.16   322.2  814.95   352.4   826.5   362.5  830.19   372.5  833.34
#Mann= 3 , 0 , 0
       0      .1       0     136    .045       0     146      .1       0
Bank Sta=136,146
XS Rating Curve= 0 ,0
Exp/Cntr=0.3,0.1

Type RM Length L Ch R = 1 ,18362   ,150.8,152.2,153.5
XS GIS Cut Line= 2
     1604140.234      398584.072     1604254.419      398910.695
#Sta/Elev= 30
     9.9  838.73    19.8  834.96    29.7  830.96    39.5   826.6    49.4  821.88
    59.3  816.86      89  801.42    98.9  796.45   118.6  787.09   128.5  783.48
   133.4  782.91   138.4  782.34   143.4  782.95   148.3  783.55   158.2  785.83
   168.1  787.84   177.9  789.08   187.8  789.86   207.6  791.13   217.5  791.89
   237.3  793.59     257  794.66   266.9  796.16   276.8  799.32   286.7  804.09
   306.5  815.18   316.3  820.17   326.2  823.55   336.1  825.65     346  827.57
#Mann= 3 , 0 , 0
       0      .1       0   133.4    .045       0   143.4      .1       0
Bank Sta=133.4,143.4
XS Rating Curve= 0 ,0
Exp/Cntr=0.3,0.1

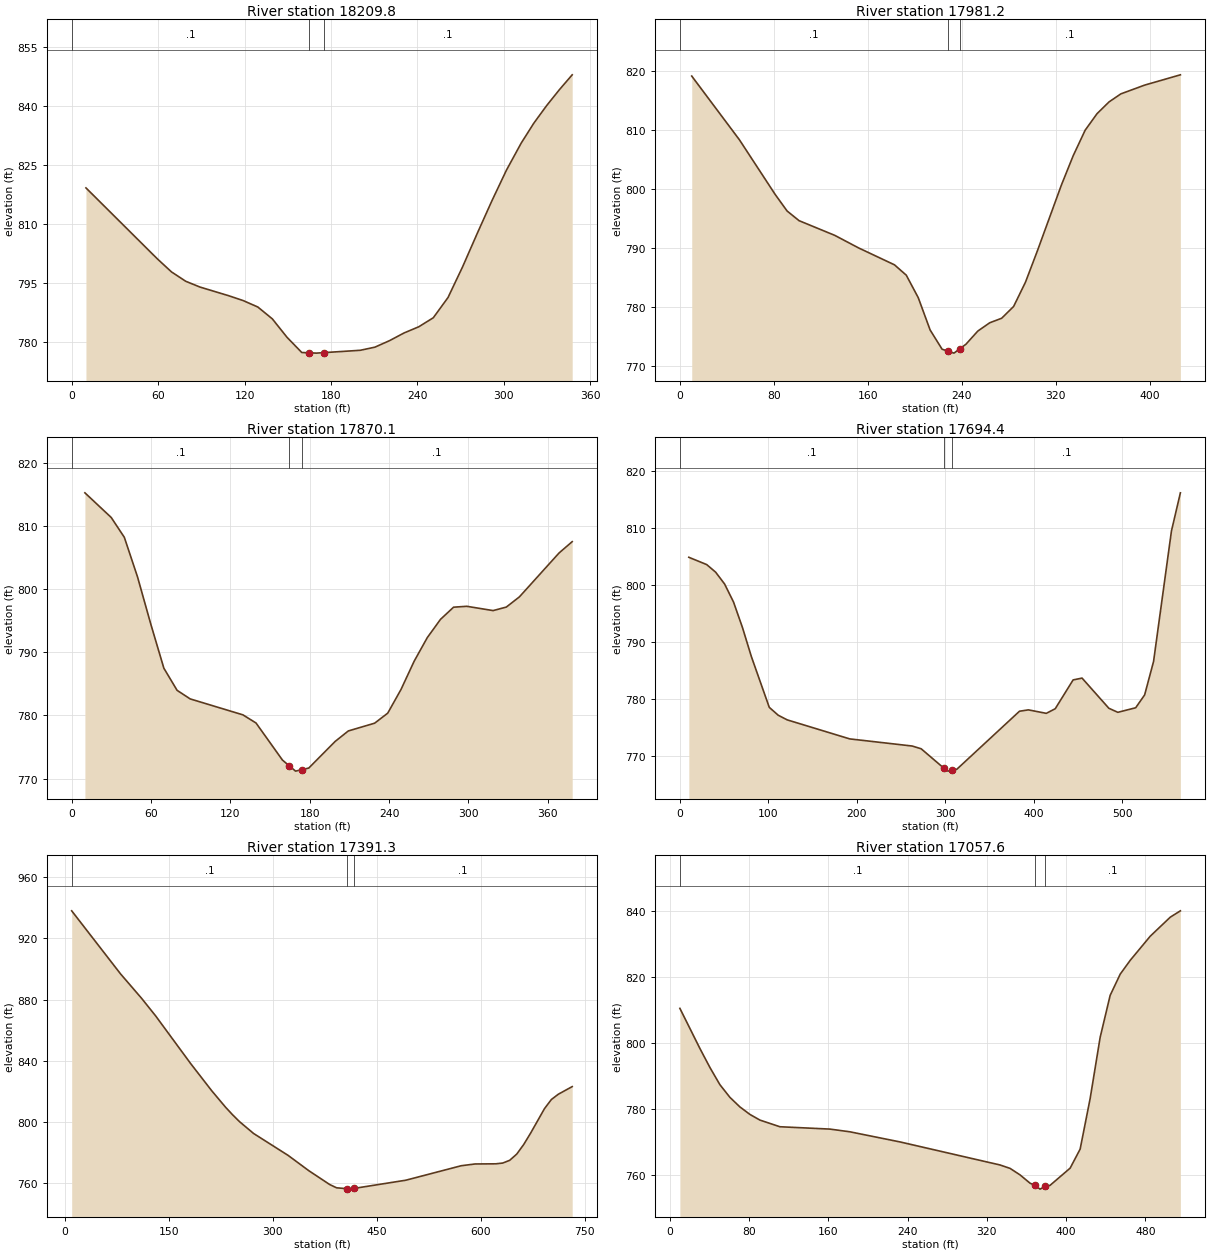
Type RM Length L Ch R = 1 ,18209.8 ,207.3,228.6,249.9
XS GIS Cut Line= 4
     1604061.467      398617.834     1604032.221      398722.716
     1604086.679      398918.361     1604083.654      398953.658
#Sta/Elev= 30
     9.9  819.22    59.4  801.19    69.3  797.84    79.2  795.46    89.1  793.99
   108.9   791.8     119  790.56   129.2  788.92   139.3  785.89   149.5   781.2
   159.7  777.35   164.8  777.27   169.8  777.19   174.8  777.31   200.3  777.91
   210.4   778.7   220.6  780.36   230.7  782.32   240.9  783.89     251  786.19
   261.2  791.33   271.3  799.12   281.5  807.65   291.7  815.96   301.8  823.76
     312  830.61   320.8   835.7   329.7  840.17   338.5  844.19   347.4  847.98
#Mann= 3 , 0 , 0
       0      .1       0   164.8    .045       0   174.8      .1       0
Bank Sta=164.8,174.8
XS Rating Curve= 0 ,0
Exp/Cntr=0.3,0.1

Type RM Length L Ch R = 1 ,17981.2 ,112.7,111.1,109.5
XS GIS Cut Line= 2
      1604007.46      398610.626     1603704.737      398910.695
#Sta/Elev= 30
    10.1  819.19    50.7  808.39    81.2  799.11    91.3  796.32   101.5  794.68
   131.9  792.19   152.2  790.06   182.7   787.2   192.8  785.44     203  781.62
   213.1  776.15   223.3  772.89   228.4  772.56   233.4  772.23   238.4  772.97
   243.6  773.74   253.7  775.97   263.9  777.38     274  778.14   284.2  780.14
   294.3  784.26   304.5   789.6   324.8  800.68   334.9  805.68   345.1  810.01
   355.2  812.81   365.4   814.8   375.5  816.17   395.8  817.66   426.2   819.4
#Mann= 3 , 0 , 0
       0      .1       0   228.4    .045       0   238.4      .1       0
Bank Sta=228.4,238.4
XS Rating Curve= 0 ,0
Exp/Cntr=0.3,0.1

Type RM Length L Ch R = 1 ,17870.1 ,180.3,175.7,171.1
XS GIS Cut Line= 2
     1603869.376       398573.45     1603622.417      398860.241
#Sta/Elev= 30
      10  815.29    29.9  811.38    39.8  808.24    49.8  801.95    59.8  794.49
    69.7  787.49    79.7  783.98    89.6  782.62   129.5  780.09   139.4   778.8
   159.4  772.92   164.3  772.05   169.3  771.17   174.3  771.41   179.3  771.66
   199.2  775.87   209.2  777.54   229.1  778.77     239  780.36     249   784.1
     259   788.6   268.9  792.33   278.9  795.23   288.8  797.16   298.8   797.3
   318.7  796.62   328.7  797.18   338.6   798.8   368.5  805.74   378.5  807.55
#Mann= 3 , 0 , 0
       0      .1       0   164.3    .045       0   174.3      .1       0
Bank Sta=164.3,174.3
XS Rating Curve= 0 ,0
Exp/Cntr=0.3,0.1

Type RM Length L Ch R = 1 ,17694.4 ,326.2,303.1,280
XS GIS Cut Line= 2
     1603757.915      398330.417     1603494.954      398831.031
#Sta/Elev= 30
    10.1  804.81    30.3  803.53    40.4   802.2    50.5  800.13    60.6  796.97
    70.7   792.5    80.8  787.39     101   778.5   111.1  777.12   121.2  776.31
   191.9  772.97   262.5  771.72   272.6  771.24   297.9  767.89   302.9  767.32
   307.9  767.49     313  767.66   383.7  777.82   393.8  778.06     414  777.45
   424.1  778.26   444.3  783.31   454.4  783.63   484.7  778.34   494.8  777.63
     515  778.43   525.1  780.68   535.2  786.55   555.4  809.42   565.5  816.11
#Mann= 3 , 0 , 0
       0      .1       0   297.9    .045       0   307.9      .1       0
Bank Sta=297.9,307.9
XS Rating Curve= 0 ,0
Exp/Cntr=0.3,0.1

Type RM Length L Ch R = 1 ,17391.3 ,321,333.7,345.6
XS GIS Cut Line= 4
     1603314.382      398161.852     1603285.172       398432.71
     1603452.467      398669.047     1603460.433      398838.997
#Sta/Elev= 30
    10.1  938.12    80.7  896.74     111  880.77   131.2   869.3   181.6  838.14
   211.9  820.38   232.1  809.45   242.2  804.52   252.2  800.03   272.4   792.3
   322.4  777.89   352.3  767.85   382.3  758.83   392.2  756.68   407.2  756.12
  412.18  755.82   417.2  756.28   492.1  761.66     572  771.14     592   772.3
     622   772.4     632  772.91     642  774.71   652.1  778.77   662.1  785.02
   672.1  792.49   692.1  808.52   702.1  814.54   712.1  817.98   732.1  822.98
#Mann= 3 , 0 , 0
    10.1      .1       0   407.2    .045       0   417.2      .1       0
Bank Sta=407.2,417.2
XS Rating Curve= 0 ,0
Exp/Cntr=0.3,0.1

Type RM Length L Ch R = 1 ,17057.6 ,345.5,348.2,351.6
XS GIS Cut Line= 3
     1603205.508      398384.911      1603216.13      398687.635
     1603213.474      398900.073
#Sta/Elev= 30
    10.1  810.57    30.3  798.42    40.4  792.67    50.5  787.45    60.6  783.61
    70.7  780.71    80.8  778.44    90.9  776.72   111.1   774.7   161.6  773.99
   181.7  773.17   232.2  770.11   333.3  763.12   343.4  762.09   353.5  760.12
   363.6   757.6   368.7  756.93   373.7   755.8   378.7   756.6   383.8  756.94
   404.1  762.16   414.2  767.93   424.3  783.25   434.4  801.79   444.5  814.51
   454.7  820.96   464.8  825.14     485  832.44   505.2   838.2   515.4  840.12
#Mann= 3 , 0 , 0
    10.1      .1       0   368.7    .045       0   378.7      .1       0
Bank Sta=368.7,378.7
XS Rating Curve= 0 ,0
Exp/Cntr=0.3,0.1

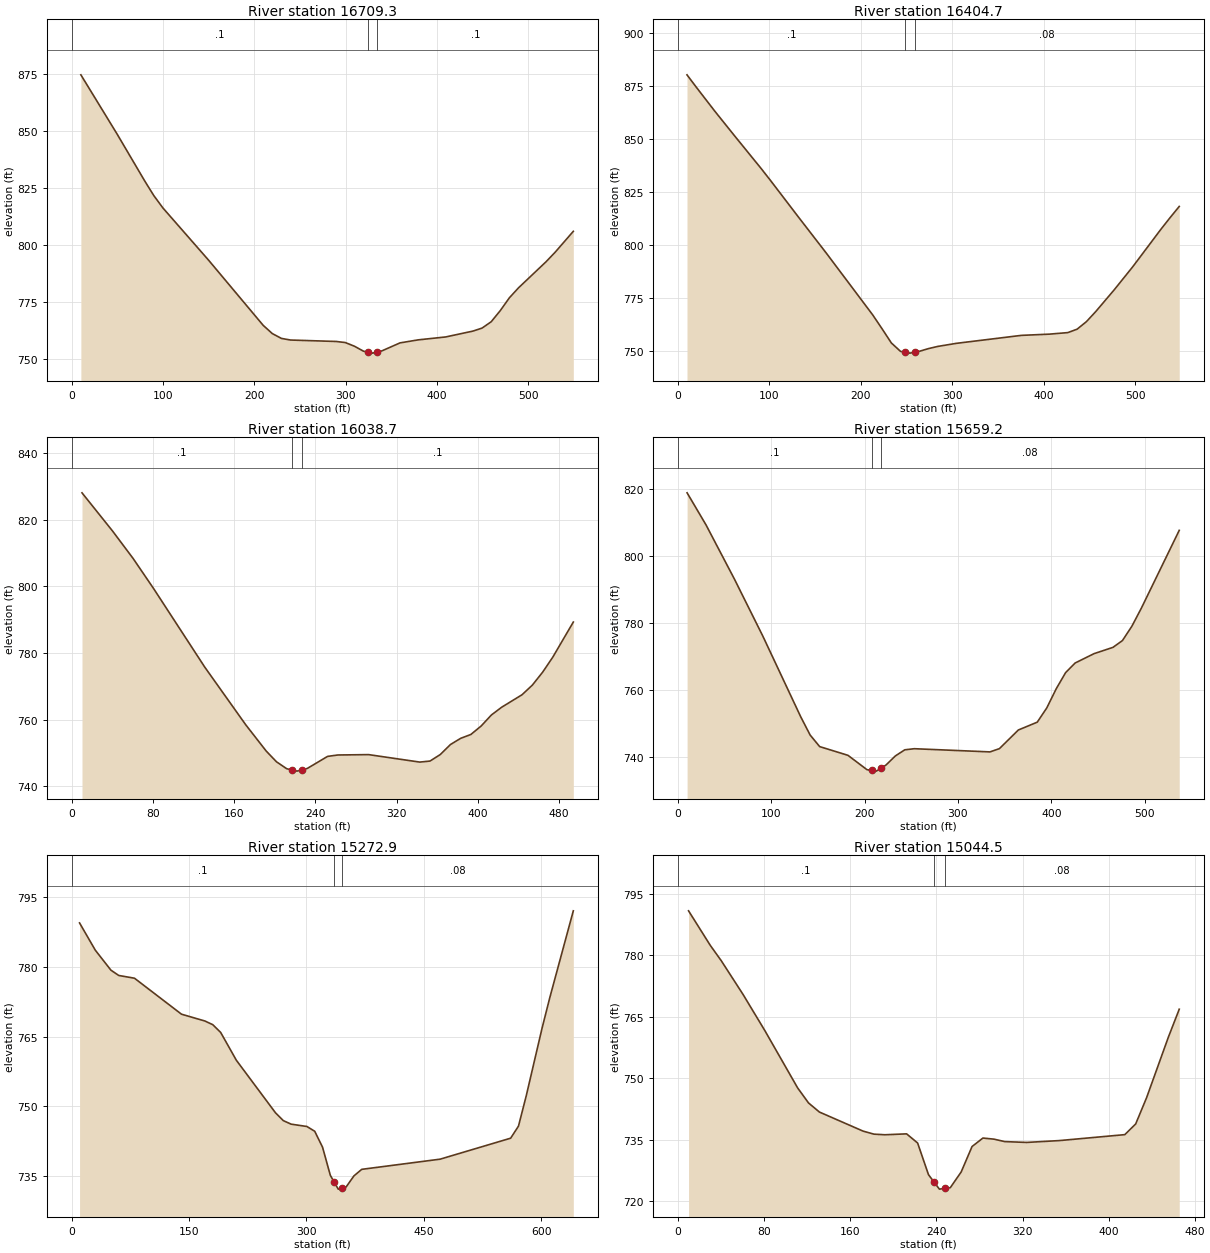
Type RM Length L Ch R = 1 ,16709.3 ,300.3,304.6,308.5
XS GIS Cut Line= 2
     1602955.894      398358.357     1602836.397      398894.762
#Sta/Elev= 30
      10  874.66      50  848.49    79.9  828.17    89.9  821.72    99.9  816.28
   149.9  793.41   209.8   764.8   219.8  761.19   229.8  759.08   239.8  758.37
   289.8  757.74   299.8  757.26   309.7  755.67   319.7  753.48   324.7  753.05
   329.7  752.63   334.7  753.11   339.7  753.59   359.7  757.12   379.7  758.45
   409.7  759.72   439.6  762.29   449.6  763.61   459.6  766.38   469.6  771.29
   479.6  776.92   489.6  781.28   519.6  792.65   529.6  796.83   549.6  806.04
#Mann= 3 , 0 , 0
       0      .1       0   324.7    .045       0   334.7      .1       0
Bank Sta=324.7,334.7
XS Rating Curve= 0 ,0
Exp/Cntr=0.3,0.1

Type RM Length L Ch R = 1 ,16404.7 ,366.3,366.1,365.8
XS GIS Cut Line= 2
      1602711.59      398310.558     1602509.775      398820.409
#Sta/Elev= 30
    10.2  880.47    20.3  874.68    40.6  863.33    60.9  852.41    91.4  836.21
   101.5  830.65     132  813.42   162.5  796.39   213.2  767.27   223.4  760.74
   233.6  754.03   243.7  750.03   248.9  749.62   253.9  749.23   258.9  749.64
     264  750.06   274.2  751.36   284.3  752.39   304.6  753.84   375.7   757.6
   406.2  758.18   426.5  758.91   436.6  760.51   446.8  764.06     457  768.81
   477.3  779.13   497.6  790.02     528  807.49   538.2  813.07   548.3   818.4
#Mann= 3 , 0 , 0
       0      .1       0   248.9    .045       0   258.9     .08       0
Bank Sta=248.9,258.9
XS Rating Curve= 0 ,0
Exp/Cntr=0.3,0.1

Type RM Length L Ch R = 1 ,16038.7 ,389,379.5,370
XS GIS Cut Line= 2
     1602355.757      398212.306     1602180.496      398674.358
#Sta/Elev= 30
    10.1  828.02    40.3  816.53    60.5  808.32    80.7  799.29   131.1  775.74
   171.4  758.48   191.6  750.59   201.7  747.38   211.8  745.29   216.9  744.93
   221.9  744.57   226.9  744.96     232  745.36   252.1  748.99   262.2  749.41
   292.5  749.52   342.9  747.28     353  747.59   363.1  749.54   373.2  752.56
   383.2   754.4   393.3  755.57   403.4   758.1   413.5  761.41   423.6  763.73
   443.7  767.48   453.8  770.35   463.9  774.21     474  778.76   494.2  789.27
#Mann= 3 , 0 , 0
       0      .1       0   216.9    .045       0   226.9      .1       0
Bank Sta=216.9,226.9
XS Rating Curve= 0 ,0
Exp/Cntr=0.3,0.1

Type RM Length L Ch R = 1 ,15659.2 ,401.7,386.3,370.9
XS GIS Cut Line= 2
     1601889.334      398138.184      1601949.47      398671.702
#Sta/Elev= 30
    10.1  818.84    30.4  809.26    60.8  793.11    91.2  776.12   131.7  752.11
   141.8  746.66     152  743.21   182.3  740.61   202.6  736.34   207.7  736.11
   212.7   735.9   217.7  736.78   222.9  737.69     233  740.42   243.1  742.25
   253.3  742.58   334.3  741.63   344.4   742.6   364.7  748.16   384.9  750.49
   395.1  754.73   405.2  760.43   415.3  765.27   425.5  768.13   445.7  770.91
     466  772.79   476.1  774.81   486.2  779.08   496.4  784.49   536.9  807.66
#Mann= 3 , 0 , 0
       0      .1       0   207.7    .045       0   217.7     .08       0
Bank Sta=207.7,217.7
XS Rating Curve= 0 ,0
Exp/Cntr=0.3,0.1

Type RM Length L Ch R = 1 ,15272.9 ,228.9,228.5,228
XS GIS Cut Line= 2
     1601309.501      398254.793     1601803.419      398663.736
#Sta/Elev= 30
      10  789.49    30.1  783.63    50.1  779.32    60.1  778.18    80.2  777.59
   140.3  769.84   170.3  768.37   180.3  767.58   190.4  765.91   210.4  759.93
   260.5   748.6   270.5  746.92   280.5  746.16   300.6  745.66   310.6  744.63
   320.6  741.21   330.6  735.13   335.7  733.63   340.7  732.17   345.7  732.39
   350.7  732.62   360.7  735.01   370.7  736.43   470.9  738.62   561.1  743.14
   571.1  745.74   581.1  752.32   601.2   766.8   611.2  773.45   641.2   792.1
#Mann= 3 , 0 , 0
       0      .1       0   335.7    .045       0   345.7     .08       0
Bank Sta=335.7,345.7
XS Rating Curve= 0 ,0
Exp/Cntr=0.3,0.1

Type RM Length L Ch R = 1 ,15044.5 ,302.6,302.2,301.7
XS GIS Cut Line= 2
     1601240.459      398501.752     1601606.914      398788.543
#Sta/Elev= 30
    10.1  790.82    30.3  782.38    40.5  778.63    60.7  770.41    80.9   761.6
   111.3  747.63   121.4  743.96   131.5  741.74     172  737.09   182.1  736.35
   192.2   736.2   212.4  736.42   222.6  734.19   232.7  726.46   237.8  724.68
   242.8  722.94   247.8  723.11   252.9  723.29     263  727.12   273.1  733.33
   283.2   735.4   293.4  735.13   303.5  734.53   323.7  734.33   354.1  734.78
   414.8  736.23   424.9  738.84     435  745.23   455.2  759.99   465.3  766.82
#Mann= 3 , 0 , 0
       0      .1       0   237.8    .045       0   247.8     .08       0
Bank Sta=237.8,247.8
XS Rating Curve= 0 ,0
Exp/Cntr=0.3,0.1

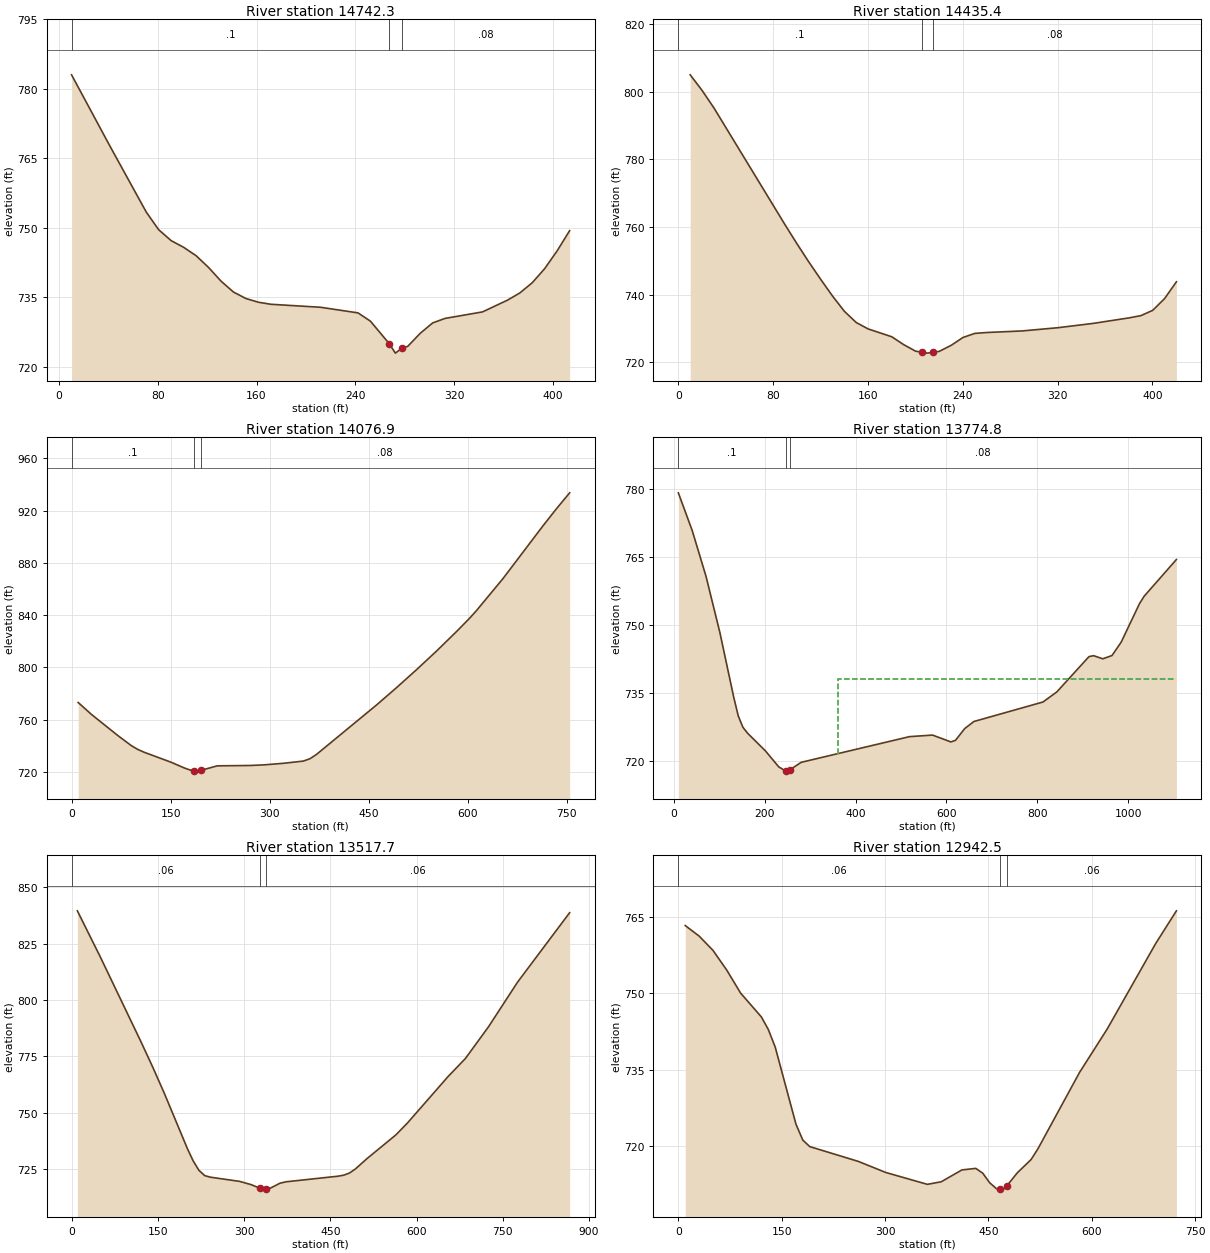
Type RM Length L Ch R = 1 ,14742.3 ,309.2,307,304.7
XS GIS Cut Line= 2
     1601062.543      398748.711     1601394.476       398995.67
#Sta/Elev= 30
    10.1  783.01    40.4  768.01    70.6  753.39    80.7  749.56    90.8  747.21
   100.9  745.77     111  743.96   121.1  741.42   131.2  738.47   141.3  736.11
   151.4  734.71   161.5  733.91   171.5  733.47   211.9  732.82   242.2  731.61
   252.3  729.82   267.5  724.97   272.5  722.92   277.5  723.92   282.5  724.38
   292.6  727.19   302.7  729.44   312.8  730.42   343.1  731.82   363.3  734.35
   373.4  735.92   383.5  738.14   393.5  741.17   403.6  745.01   413.7  749.36
#Mann= 3 , 0 , 0
    10.1      .1       0   267.5    .045       0   277.5     .08       0
Bank Sta=267.5,277.5
XS Rating Curve= 0 ,0
Exp/Cntr=0.3,0.1

Type RM Length L Ch R = 1 ,14435.4 ,360.1,358.4,356.7
XS GIS Cut Line= 2
     1600893.369      399022.892     1601254.513      399237.985
#Sta/Elev= 30
      10  805.02      20  800.42      30  795.24    90.1  760.62   100.1  755.03
   110.1  749.65   120.1  744.51   130.1  739.57   140.1  735.05   150.1  731.73
   160.1  729.84   180.1  727.51   190.2  725.17   200.2  723.25   205.2  722.96
   210.2  722.67   215.2  722.94   220.2   723.2   230.2  724.97   240.2   727.3
   250.2  728.51   260.2  728.77   290.2  729.24   320.3  730.19   350.3  731.48
   380.3   733.1   390.3  733.76   400.3  735.33   410.3   738.8   420.3  743.78
#Mann= 3 , 0 , 0
       0      .1       0   205.2    .045       0   215.2     .08       0
Bank Sta=205.2,215.2
XS Rating Curve= 0 ,0
Exp/Cntr=0.3,0.1

Type RM Length L Ch R = 1 ,14076.9 ,283.4,302.2,320.9
XS GIS Cut Line= 3
     1600727.953       399359.17     1601034.406      399508.467
     1601410.409      399680.482
#Sta/Elev= 30
      10  773.16    30.1  764.02    70.2  747.81    90.2  740.25   100.3  737.23
   110.3     735   150.4  727.51   170.4  723.12   180.5   721.3   185.5  720.97
   190.5  720.63   195.5  721.16   220.6  724.67   270.7  724.95   290.8   725.4
   320.8  726.61     351  728.31   361.1  730.11   371.1  733.46   461.9  771.23
   492.2  784.49   522.4   798.2   552.7  812.44   582.9  827.33   603.1  837.72
   613.2  843.39   653.5  867.97     714  908.28   734.2  921.22   754.4  933.56
#Mann= 3 , 0 , 0
       0      .1       0   185.5    .045       0   195.5     .08       0
Bank Sta=185.5,195.5
XS Rating Curve= 0 ,0
Exp/Cntr=0.3,0.1

Type RM Length L Ch R = 1 ,13774.8 ,264,257.1,250.3
XS GIS Cut Line= 4
     1600690.776      399404.612     1600680.155      399566.596
     1600730.608      399837.454     1601168.761      400341.994
#Sta/Elev= 30
    10.1  779.17    40.6  770.86      71  760.77   101.5  748.38   131.9  734.16
     142  729.99   152.2  727.51   162.3  726.22   201.7  722.31   231.2  718.77
   245.9   717.9   250.9  717.85   255.9  718.17   280.4  719.79   518.8  725.45
   569.5  725.79     610  724.28   620.1  724.65   640.3  727.23   660.6  728.79
   812.5  733.08   842.8  735.29   913.7  743.08   923.8  743.29   944.1   742.6
   964.3  743.32   984.6  746.28  1025.1   754.8  1035.2   756.4  1106.1  764.48
#Mann= 3 , 0 , 0
    10.1      .1       0   245.9    .045       0   255.9     .08       0
#XS Ineff= 2 , 0
                           360.4          738.15
Permanent Ineff=
       F       F
Bank Sta=245.9,255.9
XS Rating Curve= 0 ,0
Exp/Cntr=0.3,0.1

Type RM Length L Ch R = 1 ,13517.7 ,563.7,575.1,586.5
XS GIS Cut Line= 2
     1600295.111      399468.344     1600730.608      400217.187
#Sta/Elev= 30
    10.1  839.52    50.4  818.85   120.9  781.32     141  770.27   161.2  758.63
   201.5  733.98   211.5  728.56   221.6  724.33   231.7  722.01   241.7  721.31
   292.1  719.47   312.3  718.02   327.4  716.44   332.4  716.02   337.4  716.03
   342.5  716.04   362.6  718.65   372.7  719.26   463.4  721.76   473.4  722.21
   483.5  723.19   493.6  724.95   513.7  729.53   564.1  740.09   584.2  745.36
   654.7  765.93     685  773.98   725.2  788.06   775.6  807.82   866.3  838.69
#Mann= 3 , 0 , 0
       0     .06       0   327.4    .045       0   337.4     .06       0
Bank Sta=327.4,337.4
XS Rating Curve= 0 ,0
Exp/Cntr=0.3,0.1

Type RM Length L Ch R = 1 ,12942.5 ,508.2,513.3,517.7
XS GIS Cut Line= 2
     1599981.766      399508.176     1599952.555      400230.464
#Sta/Elev= 30
      10  763.26    30.1   761.2    50.2   758.4    70.3  754.51    90.4     750
   120.5  745.33   130.5  742.89   140.6  739.41   170.7  724.29   180.7  721.15
   190.8  719.88     261  716.99   301.2   714.8   361.4  712.48   381.5  712.98
   411.6  715.31   431.7  715.61   441.8  714.67   451.8   712.8   461.8  711.62
   466.9  711.58   471.9  711.54   476.9   712.2     492  714.75     512  717.35
   522.1   719.5   582.3  734.44   622.5  742.97   692.8  759.73   722.9  766.15
#Mann= 3 , 0 , 0
       0     .06       0   466.9    .045       0   476.9     .06       0
Bank Sta=466.9,476.9
XS Rating Curve= 0 ,0
Exp/Cntr=0.3,0.1

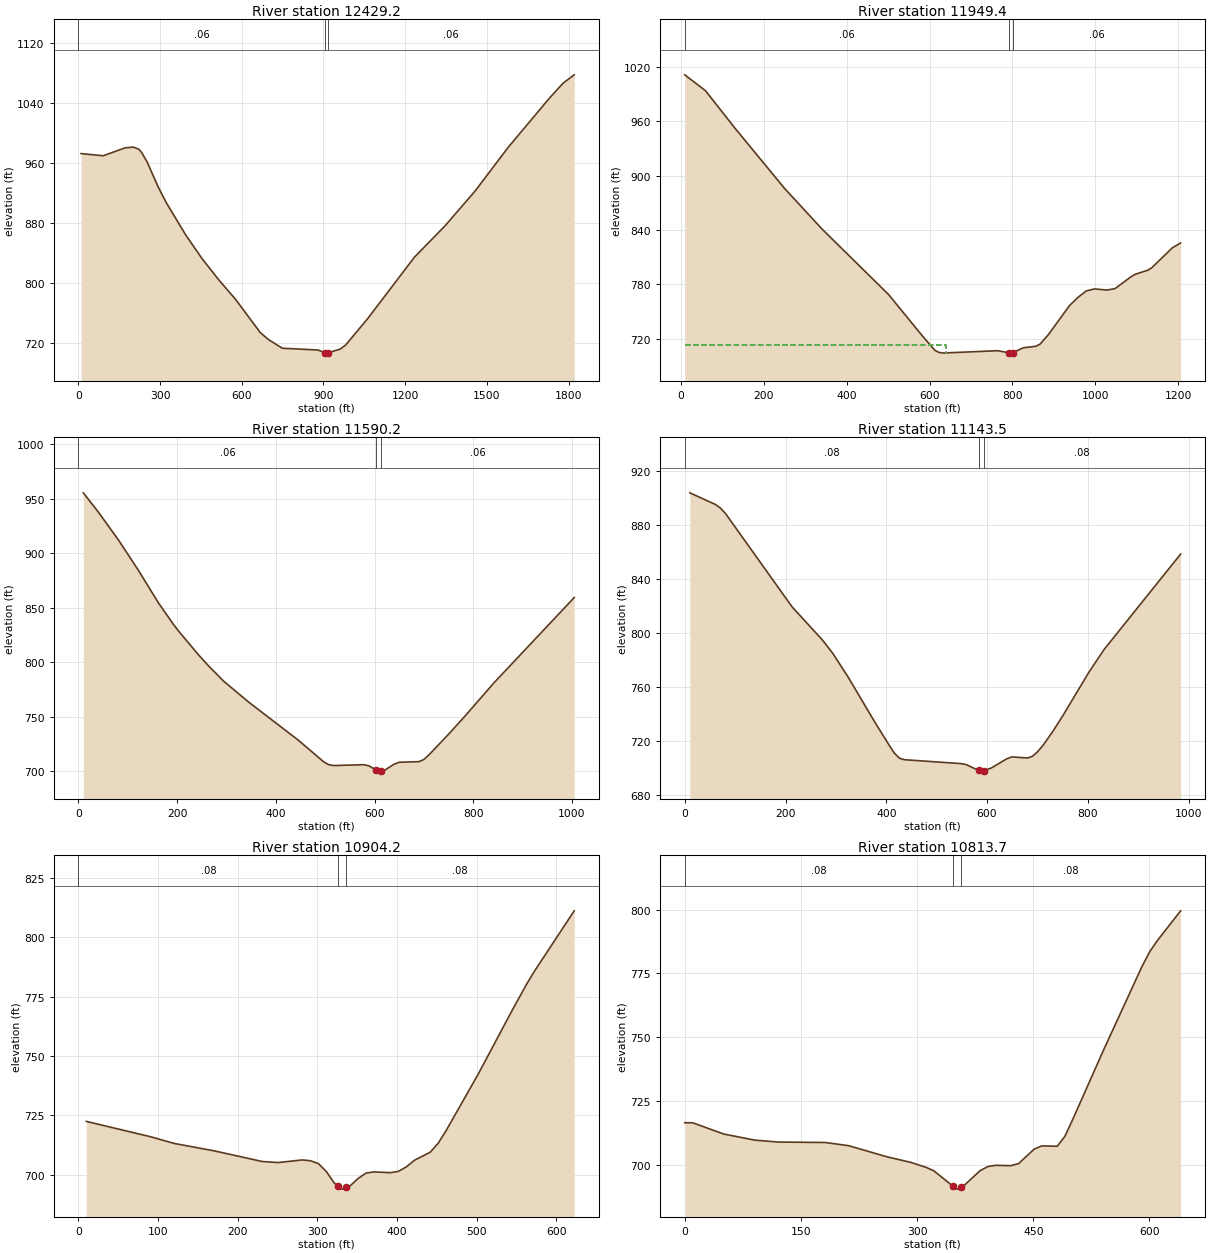
Type RM Length L Ch R = 1 ,12429.2 ,471,479.9,489.5
XS GIS Cut Line= 3
     1599733.467      398966.602     1599469.343      399838.146
     1599237.031      400717.868
#Sta/Elev= 30
    10.1  972.15    91.1  969.27     172  979.82   202.4  980.78   222.6  977.82
   232.7  973.54     253  960.73   293.4  927.58   323.8  906.28   394.6  863.69
   455.3  831.85   516.1  803.88   576.8  778.35   667.8     734   698.2   724.6
   748.8  713.08   880.3  710.67   905.7  707.04   910.7  706.55   915.7  706.88
   961.2  711.91   981.5  717.39  1062.3  752.47  1234.2  834.37  1345.4  875.63
  1456.6  922.28  1577.9  980.38  1729.6 1045.96  1780.1 1066.02  1820.6 1077.01
#Mann= 3 , 0 , 0
       0     .06       0   905.7    .045       0   915.7     .06       0
Bank Sta=905.7,915.7
XS Rating Curve= 0 ,0
Exp/Cntr=0.3,0.1

Type RM Length L Ch R = 1 ,11949.4 ,356.9,359.2,361.3
XS GIS Cut Line= 4
     1599530.335      399040.813     1599254.166      399409.923
       1598906.3      399792.311     1598850.535      400012.715
#Sta/Elev= 30
      10 1011.13    60.1  993.61   130.3  952.71   250.5  885.88   340.7   841.1
   501.5  768.68   582.6  723.18     613  707.17   623.2  704.78   633.3  704.22
   765.1  706.75   790.5  704.55   795.5  704.08   800.5  704.53   825.9  709.97
   856.3  711.63   866.4     714   886.7  724.53   937.4   756.5   957.7  765.53
   977.9  772.72   997.7  774.96  1027.4  773.64  1047.1  775.24  1086.7  788.64
  1096.6  791.19  1126.2  795.55  1136.1  798.38  1185.5  820.32  1205.3  825.61
#Mann= 3 , 0 , 0
      10     .06       0   790.5    .045       0   800.5     .06       0
#XS Ineff= 2 , 0
           640.3  713.06
Permanent Ineff=
       F       F
Bank Sta=790.5,800.5
XS Rating Curve= 0 ,0
Exp/Cntr=0.3,0.1

Type RM Length L Ch R = 1 ,11590.2 ,446.6,446.7,446.7
XS GIS Cut Line= 2
     1599248.855      398990.359     1598497.357      399656.882
#Sta/Elev= 30
    10.1  955.21    40.6  937.54    81.2     912   121.8  884.05   162.3  854.23
   192.8  834.45   202.9  828.52   243.5  806.55   263.8  796.47   294.2  782.52
     345  763.26   446.4  728.04   497.2  708.37   507.3  705.84   517.5  705.03
   578.3  705.83   588.5  704.78   603.8   700.9   608.8  699.92   613.8   700.1
   618.9  700.29   639.2  706.17   649.4  708.02     690  708.62   700.1  710.61
   710.2  714.83   750.8  734.18   781.3  749.41   842.1     781  1004.5  859.12
#Mann= 3 , 0 , 0
       0     .06       0   603.8    .045       0   613.8     .06       0
Bank Sta=603.8,613.8
XS Rating Curve= 0 ,0
Exp/Cntr=0.3,0.1

Type RM Length L Ch R = 1 ,11143.5 ,243.6,239.4,235.1
XS GIS Cut Line= 2
     1598930.022      398682.991     1598189.145      399330.926
#Sta/Elev= 30
    10.1  904.04    60.9  895.42      71  892.68    81.2  888.55   213.1  819.46
     274   794.6   294.3  784.77   324.7  767.15   375.4  735.18   405.9  716.79
     416  711.05   426.2  707.19   436.3  706.11   547.9  703.24   558.1  702.55
   583.5  698.16   588.5  697.65   593.5  697.93   608.8  700.03   639.2   706.8
   649.4  708.21   679.8   707.4     690  708.58   700.1  711.93   710.3  716.36
   730.6  727.12   750.9  739.04   801.6  770.65     832  787.71   984.2  858.61
#Mann= 3 , 0 , 0
       0     .08       0   583.5    .045       0   593.5     .08       0
Bank Sta=583.5,593.5
XS Rating Curve= 0 ,0
Exp/Cntr=0.3,0.1

Type RM Length L Ch R = 1 ,10904.2 ,88.6,90.5,92.4
XS GIS Cut Line= 2
     1598505.323      398647.803     1598133.557      399147.032
#Sta/Elev= 30
      10  722.43    90.4  715.99   120.5  713.13   170.7  710.01   230.9  705.53
     251   705.1   281.1   706.2   291.1  705.87   301.2  704.69   311.2  701.35
   321.3  696.45   326.3  695.17   331.3   693.9   336.3  694.61   341.3  695.32
   351.4  698.47   361.4   700.7   371.5  701.15   391.5  700.83   401.6  701.37
   411.6  703.25   421.7  706.03   441.7  709.46   451.8  713.29   461.8  718.67
     502   742.4   542.1  767.71   562.2  779.99   572.2  785.55   622.4  811.13
#Mann= 3 , 0 , 0
       0     .08       0   326.3    .045       0   336.3     .08       0
Bank Sta=326.3,336.3
XS Rating Curve= 0 ,0
Exp/Cntr=0.3,0.1

Type RM Length L Ch R = 1 ,10813.7 ,339.3,325.3,311.3
XS GIS Cut Line= 4
     1598470.945      398605.299     1598278.986      398811.429
     1598199.111      398900.322     1598067.703       399100.01
#Sta/Elev= 30
       0  716.63    10.1  716.63    50.3  712.22    90.5  709.83   120.7  709.08
   181.1  708.91   211.3  707.68   261.6  703.27   291.6  701.16   311.5   699.2
   321.5  697.86   346.4  691.78   351.4  690.67   356.4  691.48   361.3  692.28
   381.3  697.88   391.2  699.48   401.2  699.98   421.1  699.84   431.1  700.68
     451  706.29   460.9  707.59   480.9  707.43   490.8  711.33   500.8  717.84
   540.6     745   590.4  777.78   600.4  783.56   610.3  787.92   640.2  799.51
#Mann= 3 , 0 , 0
       0     .08       0   346.4    .045       0   356.4     .08       0
Bank Sta=346.4,356.4
XS Rating Curve= 0 ,0
Exp/Cntr=0.3,0.1