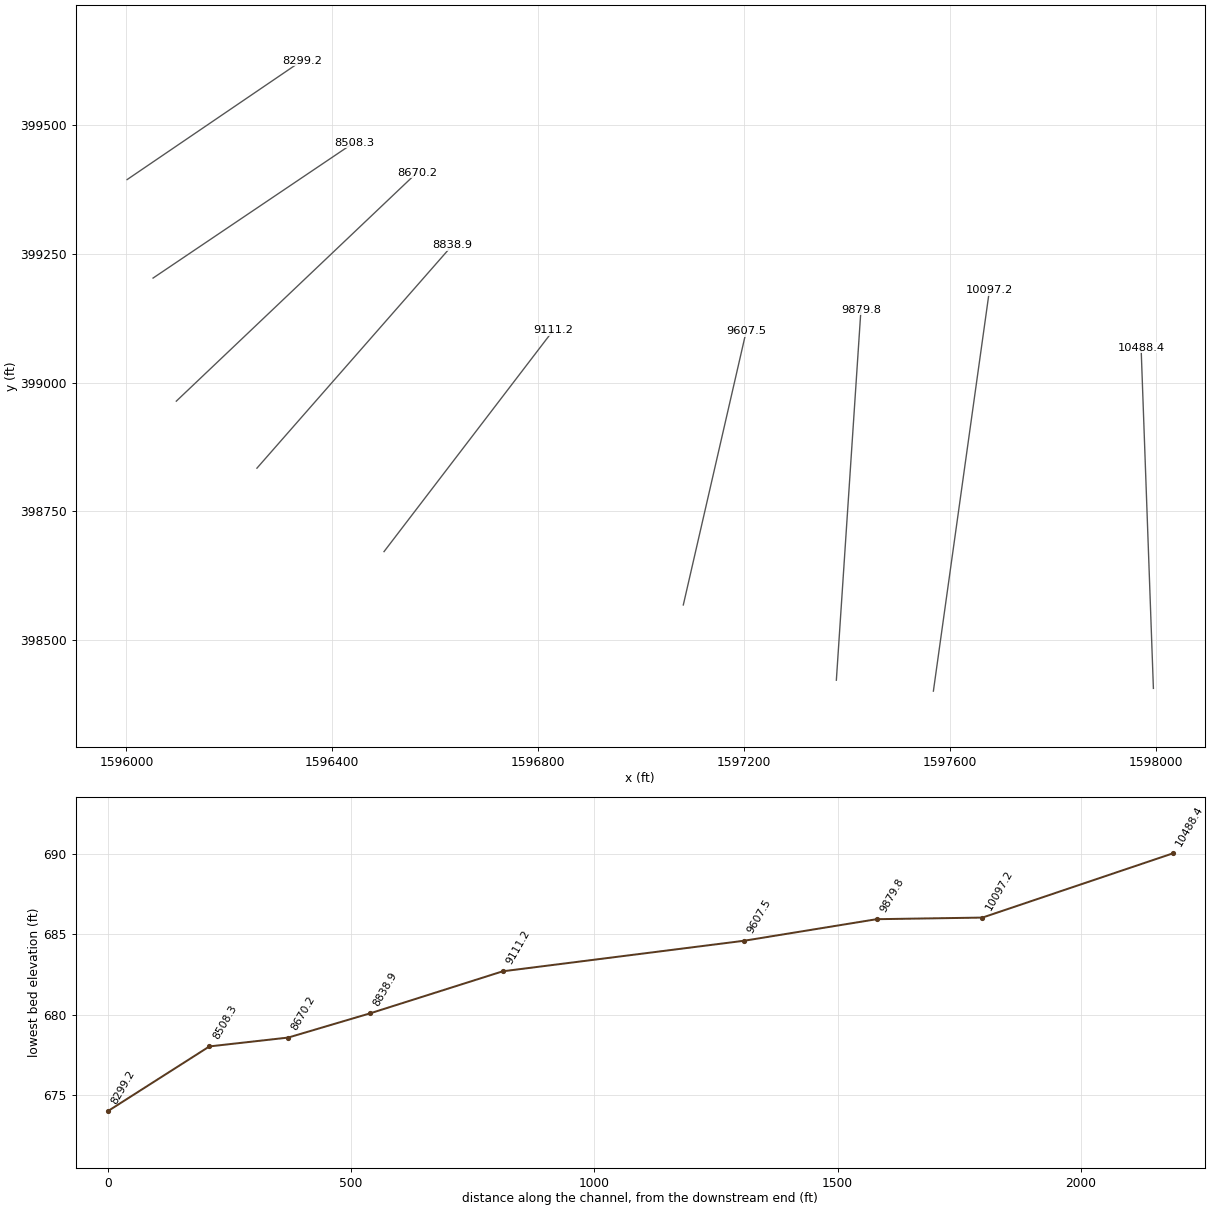
HEC-RAS study COVECR.prj: COVECR

--- COVECR.g01 (geometry) --- (continued)

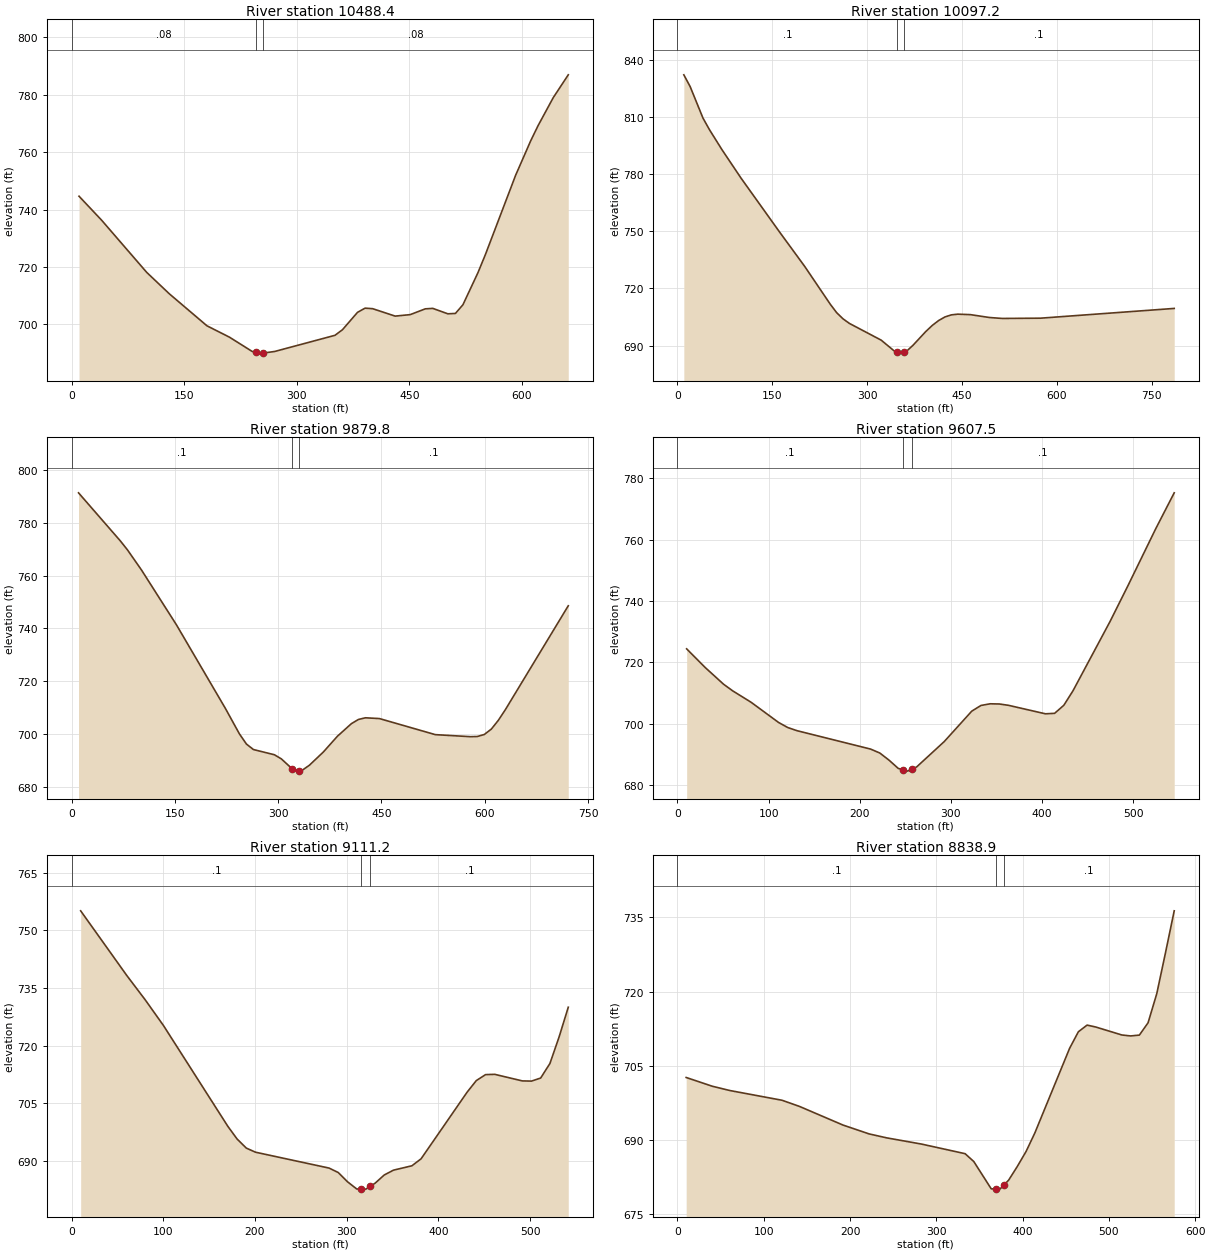
Type RM Length L Ch R = 1 ,10488.4 ,394.6,391.2,387.8
XS GIS Cut Line= 2
     1597995.473      398406.155     1597971.574      399067.368
#Sta/Elev= 30
      10  744.64    40.1  736.29   100.2  718.12   130.3  710.67   180.4  699.54
   210.5  695.56   240.6  690.62   245.6  690.32   250.6  690.03   255.6  690.06
   270.7  690.61   350.9  696.23   360.9  698.18   380.9  704.22     391  705.68
     401   705.5   431.1  702.91   451.1  703.43   471.2  705.44   481.2   705.6
   501.2  703.71   511.3  703.84   521.3  706.86   541.3  718.02   551.4  724.44
   591.5  751.93   611.5  763.88   621.5  769.25   641.6  778.94   661.6  786.88
#Mann= 3 , 0 , 0
       0     .08       0   245.6    .045       0   255.6     .08       0
Bank Sta=245.6,255.6
XS Rating Curve= 0 ,0
Exp/Cntr=0.3,0.1

Type RM Length L Ch R = 1 ,10097.2 ,216,217.4,218.8
XS GIS Cut Line= 2
     1597567.942      398400.844     1597676.816      399178.897
#Sta/Elev= 30
    10.1   832.1    20.1  825.91    40.3  809.45    50.4  803.43    70.5  792.77
   100.7  777.82   161.2  749.74   201.4  731.48   241.7   711.7   251.8  707.27
   261.9  704.02     272  701.62   322.3  692.83   342.5  687.26   347.5  686.65
   352.5  686.04   357.5  686.57   362.6  687.12   372.7  690.22   392.8   697.4
   402.9  700.55     413  703.13     423  705.02   433.1  706.11   443.2  706.49
   463.3  706.24   493.5  704.73   513.7  704.24   574.1  704.38   785.6   709.5
#Mann= 3 , 0 , 0
       0      .1       0   347.5    .045       0   357.5      .1       0
Bank Sta=347.5,357.5
XS Rating Curve= 0 ,0
Exp/Cntr=0.3,0.1

Type RM Length L Ch R = 1 ,9879.8  ,275.5,272.3,269.1
XS GIS Cut Line= 2
     1597379.403      398422.088     1597427.202      399141.721
#Sta/Elev= 30
    10.2  791.36    71.1  773.09    81.3  769.73   101.6  762.13   152.4  741.34
   223.5  709.66   243.8  700.04     254  696.19   264.1  694.12   294.6  692.14
   304.7  690.57   320.1  686.88   325.1  685.94   330.1  686.12   335.2  686.31
   345.4  688.18   365.7   693.2     386  699.14   406.3  703.91   416.5   705.5
   426.6  706.14     447  705.85   528.2  699.76     579  698.99   589.2  699.06
   599.3  699.82   609.5  701.86   619.6  705.16   629.8  709.19   721.2  748.57
#Mann= 3 , 0 , 0
       0      .1       0   320.1    .045       0   330.1      .1       0
Bank Sta=320.1,330.1
XS Rating Curve= 0 ,0
Exp/Cntr=0.3,0.1

Type RM Length L Ch R = 1 ,9607.5  ,505,496.3,487.6
XS GIS Cut Line= 2
     1597081.991      398568.139     1597204.142      399099.233
#Sta/Elev= 30
    10.1  724.43    30.3  718.39    50.5  712.93    60.6  710.75    80.7  707.05
     111  700.44   121.1  698.79   131.2  697.77   211.9  691.78     222   690.5
   232.1  688.18   242.2  685.49   247.3  685.04   252.3   684.6   257.3  685.28
   262.4  685.96   292.7  694.23   322.9  704.14     333  705.99   343.1  706.53
   353.2  706.47   363.3  706.03   403.7  703.27   413.8  703.43   423.9  706.05
     434   710.8   474.3  733.17   494.5  745.16   524.8   763.6     545  775.25
#Mann= 3 , 0 , 0
       0      .1       0   247.3    .045       0   257.3      .1       0
Bank Sta=247.3,257.3
XS Rating Curve= 0 ,0
Exp/Cntr=0.3,0.1

Type RM Length L Ch R = 1 ,9111.2  ,273.7,272.3,270.9
XS GIS Cut Line= 2
     1596500.442      398671.702     1596829.721      399101.889
#Sta/Elev= 30
      10  755.04    60.2  738.26    80.3  731.93   100.3  725.22   170.5  699.02
   180.6  695.72   190.6  693.37   200.6   692.3   280.9  688.17   290.9  687.01
     301  684.61     311  682.74     316  682.72     321   682.7     326  683.47
   331.1  684.25   341.1  686.39   351.1  687.63   371.2  688.77   381.2  690.58
   431.4   707.9   441.4  710.91   451.5  712.46   461.5  712.54   491.6  710.83
   501.6  710.78   511.6  711.58   521.7  715.36   531.7  722.26   541.7  729.98
#Mann= 3 , 0 , 0
       0      .1       0     316    .045       0     326      .1       0
Bank Sta=316,326
XS Rating Curve= 0 ,0
Exp/Cntr=0.3,0.1

Type RM Length L Ch R = 1 ,8838.9  ,170.5,168.7,166.9
XS GIS Cut Line= 2
     1596253.483      398833.686     1596633.216      399266.528
#Sta/Elev= 30
    10.1  702.64    40.4  700.87    60.6  700.01   121.2  698.04   141.4   696.8
   191.9  693.03   222.2  691.24   242.4  690.45   282.9  689.19   333.4  687.25
   343.5  685.66   363.7  680.15   368.8  680.12   373.8  680.09   378.8  680.99
   383.9  681.91     394  684.69   404.1   687.7   414.2  691.41   454.6  708.55
   464.7  711.87   474.8  713.22   484.9  712.83   515.2  711.22   525.3  711.03
   535.4   711.2   545.5  713.69   555.6  719.58   565.7  727.84   575.8   736.3
#Mann= 3 , 0 , 0
       0      .1       0   368.8    .045       0   378.8      .1       0
Bank Sta=368.8,378.8
XS Rating Curve= 0 ,0
Exp/Cntr=0.3,0.1

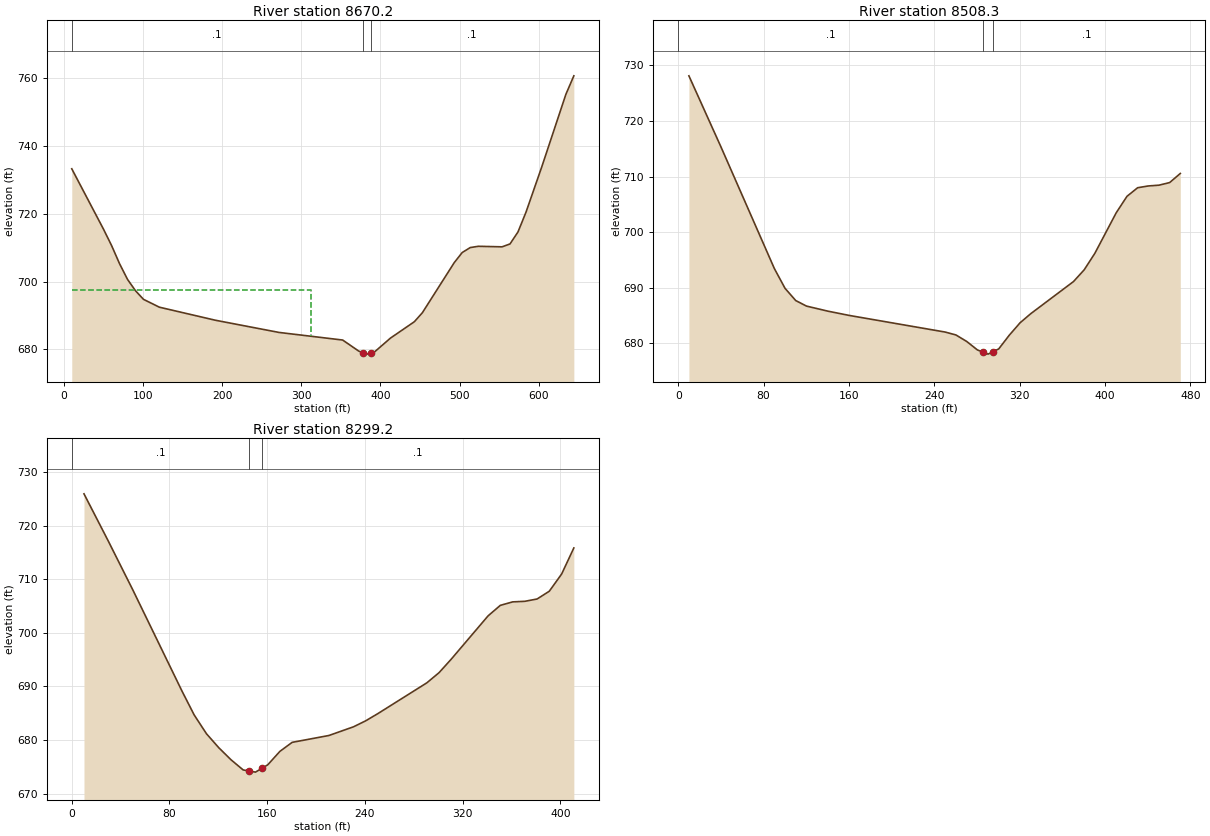
Type RM Length L Ch R = 1 ,8670.2  ,165.2,161.9,158.7
XS GIS Cut Line= 2
     1596096.811      398963.804     1596564.174      399407.268
#Sta/Elev= 30
    10.1  733.32    50.3  715.43    60.4  710.65    70.5  705.27    80.5  700.67
    90.6   697.3   100.7  694.76   120.8  692.44   191.3   688.6   271.8  684.99
   352.3  682.74   372.5  679.49   377.5  679.03   382.5  678.58   387.5  678.91
   392.6  679.24   412.7  683.32   442.9  688.16     453  690.82   493.3  705.63
   503.3  708.59   513.4  710.05   523.5  710.43   553.7  710.27   563.7  711.13
   573.8  714.69   583.9  720.53     604  734.04   634.2  755.29   644.3  760.78
#Mann= 3 , 0 , 0
    10.1      .1       0   377.5    .045       0   387.5      .1       0
#XS Ineff= 2 , 0
          312.42  697.64
Permanent Ineff=
       F       F
Bank Sta=377.5,387.5
XS Rating Curve= 0 ,0
Exp/Cntr=0.3,0.1

Type RM Length L Ch R = 1 ,8508.3  ,209,209,209.1
XS GIS Cut Line= 2
     1596051.668      399202.797     1596442.022      399465.688
#Sta/Elev= 29
      10  728.14    40.1  715.32    90.1  693.44   100.1  689.88   110.1  687.68
   120.2  686.68   140.2  685.77   160.2     685   250.3     682   260.3  681.48
   270.4  680.31   280.4  678.79   285.4  678.41   290.4  678.03   295.4   678.5
   300.4  678.97   310.4  681.46   320.4  683.67   330.4  685.31   370.5   691.1
   380.5  693.21   390.5  696.18   410.5  703.47   420.6  706.44   430.6  707.99
   440.6  708.31   450.6  708.45   460.6  708.92   470.6  710.56
#Mann= 3 , 0 , 0
       0      .1       0   285.4    .045       0   295.4      .1       0
Bank Sta=285.4,295.4
XS Rating Curve= 0 ,0
Exp/Cntr=0.3,0.1

Type RM Length L Ch R = 1 ,8299.2  ,8280.4,8299.2,8318
XS GIS Cut Line= 2
     1596001.214      399393.991     1596341.114      399625.017
#Sta/Elev= 30
      10  725.97    30.1  717.06    50.1  707.97    90.2  689.15   100.2  684.68
   110.3  681.16   120.3  678.57   130.3  676.32   140.3  674.41   145.4   674.2
   150.4     674   155.4  674.68   160.4  675.36   170.4  677.88   180.4  679.56
   210.5  680.84   230.6  682.46   240.6  683.58   250.6  684.93   290.7  690.68
   300.7  692.58   310.7  695.11   340.8  703.18   350.8  705.14   360.9  705.79
   370.9   705.9   380.9  706.33   390.9  707.78     401  710.99     411  715.86
#Mann= 3 , 0 , 0
       0      .1       0   145.4    .045       0   155.4      .1       0
Bank Sta=145.4,155.4
XS Rating Curve= 0 ,0
Exp/Cntr=0.3,0.1

Chan Stop Cuts=-1
Use User Specified Reach Order=0